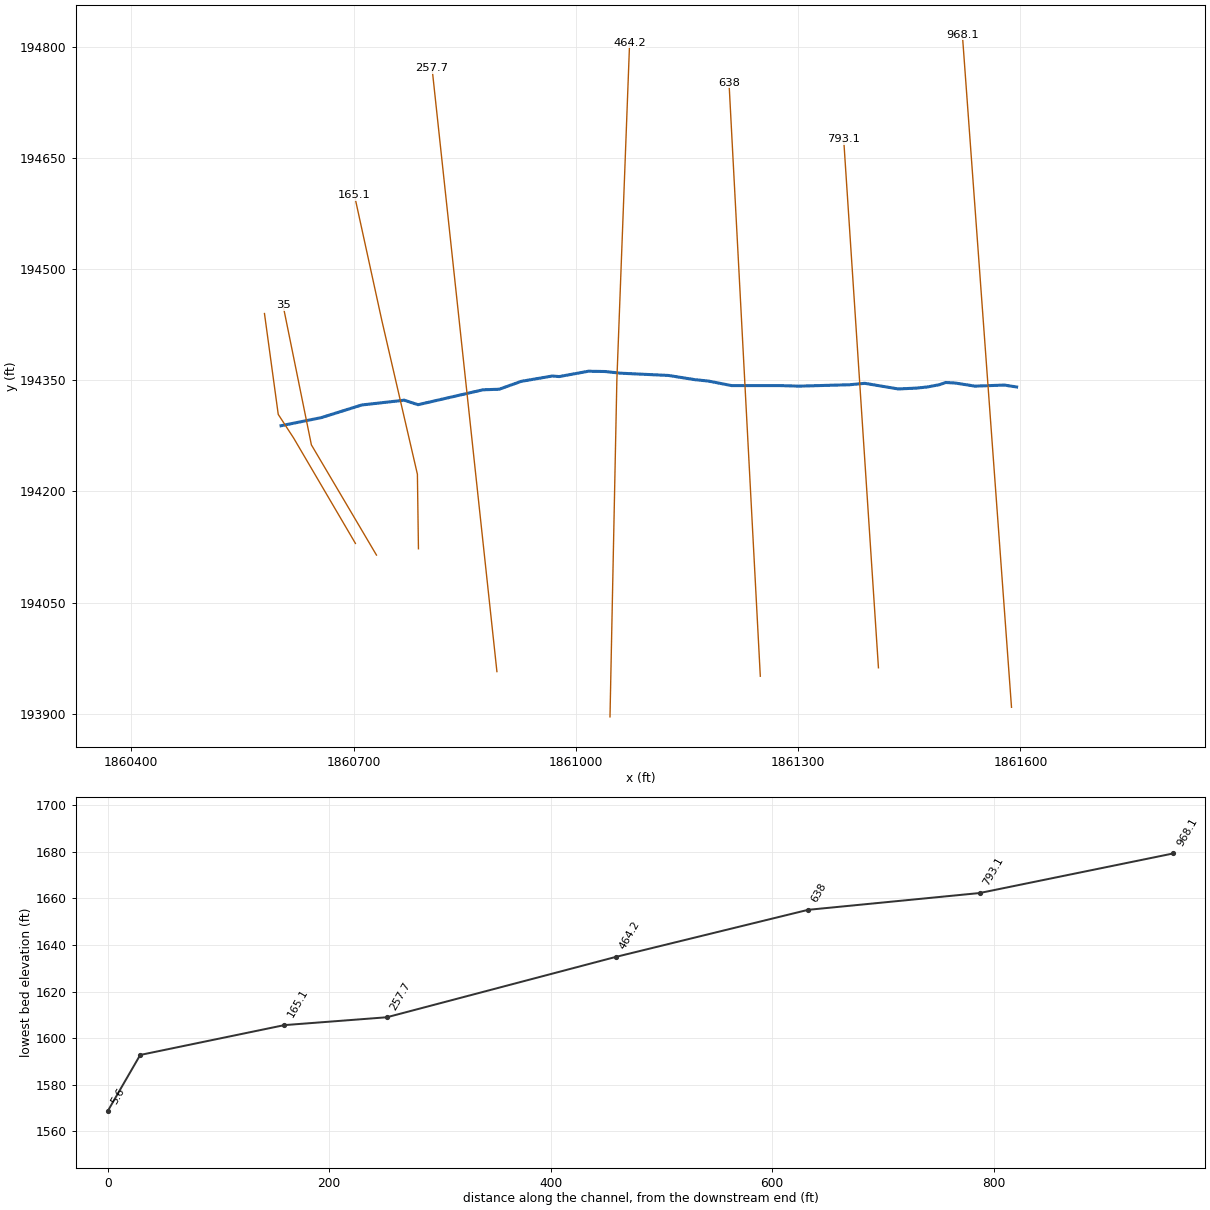
--- LambertBr2.prj (project) ---

Proj Title=LambertBr2
Current Plan=p01
Default Exp/Contr=0,0
English Units
Geom File=g01
Flow File=f01
Plan File=p01
BEGIN DESCRIPTION:
END DESCRIPTION:
DSS Export Rating Curves= 0
DSS Export Rating Curve Sorted= 0
DSS Export Volume Flow Curves= 0
DXF OffsetX= 0
DXF OffsetY= 0
DXF ScaleX= 0
DXF ScaleY= 0

--- LambertBr2.p01 (plan) ---

Plan Title=Floodplain
Program Version=4.00
Geom File=g01
Flow File=f01
K Sum by GR=0
Std Step Tol=0.01
Critical Tol=0.01
Num of Std Step Trials=20
Max Error Tol=0.3
Flow Tol Ratio=0.001
Split Flow NTrial=30
Split Flow Tol=0.02
Split Flow Ratio=0.02
Log Output Level=0
Friction Slope Method=1
Unsteady Friction Slope Method=2
Unsteady Bridges Friction Slope Method=1
Global Log Level=0
CheckData=False
Run HTab=0
Run UNet=0
Run PostProcess=0
UNET Theta=0
UNET Theta Warmup=0
UNET ZTol=0
UNET ZSATol=0
UNET MxIter=0
UNET MaxInSteps=0
UNET DtIC=0
UNET DtMin=0
UNET MaxCRTS=0
UNET WFStab=0
UNET SFStab=0
UNET WFX=0
UNET SFX=0
UNET DSS MLevel=0
UNET DZMax Abort=0
UNET Convert EG Bridges=0
UNET Use Existing IB Tables=0
UNET Froude Limit=0
UNET Froude Power=0
Write IC File=0
Echo Input=False
Echo Output=False
Write Detailed=0

--- LambertBr2.f01 (steady flow) ---

Flow Title=NFF Regression Equation
Program Version=4.00
Number of Profiles=1
Profile Names=P100yr
River Rch & RM=LambertBr2,Main      ,968.1
554.2936
River Rch & RM=LambertBr2,Main      ,165.1
572.6294
Boundary for River Rch & Prof#=LambertBr2,Main      ,1
Up Type=0
Dn Type=3
Dn Slope=0.336801

--- LambertBr2.g01 (geometry) ---

Geom Title=USGS 10m DEM
Program Version=4.00

River Reach=LambertBr2     ,Main
Reach XY= 30
     1861594.877      194340.901     1861578.254      194343.473
     1861538.712      194342.040     1861512.147      194346.215
     1861499.243      194346.974     1861490.515      194343.937
     1861474.197      194340.901     1861459.776      194339.384
     1861435.108      194338.245     1861389.948      194345.835
     1861369.455      194343.937     1861301.524      194342.040
     1861274.580      194342.799     1861210.065      194342.799
     1861178.946      194348.871     1861160.730      194350.769
     1861125.057      194356.461     1861060.542      194359.497
     1861039.290      194361.774     1861016.899      194362.154
     1860977.431      194354.943     1860968.165      194355.702
     1860926.199      194348.492     1860896.598      194337.866
     1860874.587      194337.106     1860786.922      194316.993
     1860768.327      194323.065     1860711.022      194316.614
     1860656.374      194299.536     1860602.097      194288.591

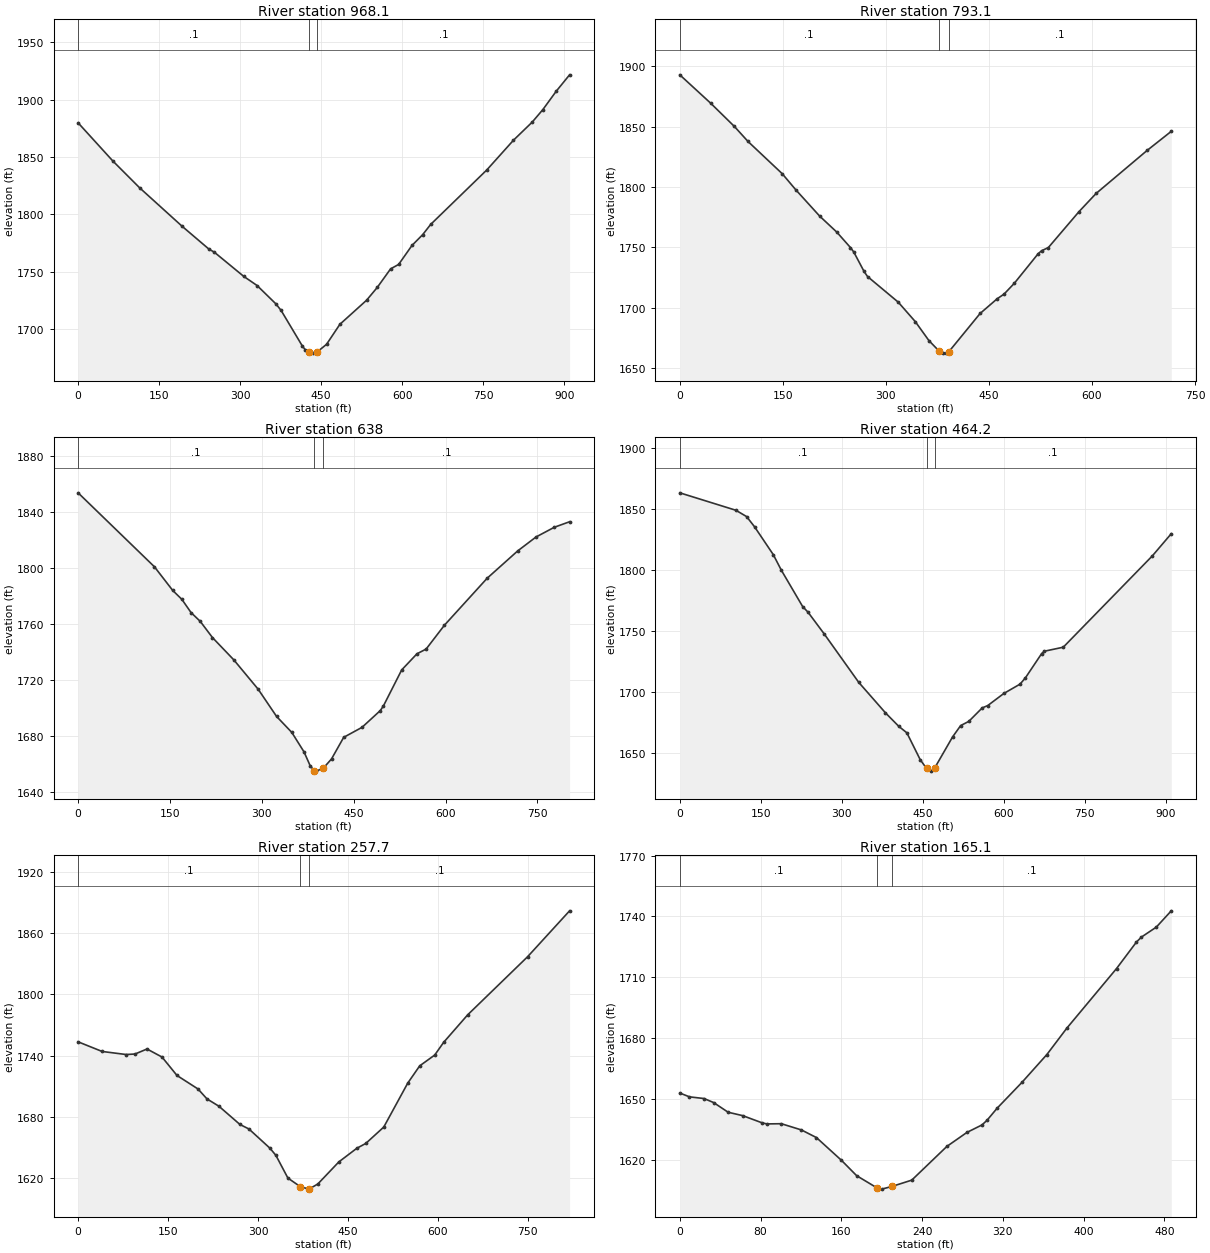
Type RM Length L Ch R = 1 ,968.1,175.1,175,175
XS GIS Cut Line= 3
     1861587.979      193908.588     1861554.826      194362.379
     1861521.673      194816.170
#Sta/Elev= 30
       0 1879.80    64.3 1846.57   113.8 1823.26   192.9 1789.58   242.3 1769.80
   252.2 1767.15   306.6 1746.11   331.4 1738.11   366.0 1722.24   375.9 1716.41
   415.4 1685.28   420.4 1682.30   427.6 1680.50   435.2 1679.25   442.6 1680.28
   460.0 1686.92   484.7 1704.35   534.1 1725.30   553.9 1736.46   578.6 1752.63
   593.5 1756.49   618.2 1773.03   638.0 1782.42   652.8 1791.33   756.7 1838.76
   806.1 1864.66   840.8 1880.42   860.5 1891.31   885.3 1907.34   910.0 1921.60
#Mann= 3 , 0 , 0
       0     0.1       0   427.6   0.045       0   442.6     0.1       0
Bank Sta=   427.6,   442.6
Exp/Cntr=0.3,0.1

Type RM Length L Ch R = 1 ,793.1,155.3,155,154.8
XS GIS Cut Line= 2
     1861408.391      193961.920     1861361.436      194675.637
#Sta/Elev= 30
       0 1892.91    44.7 1869.53    79.5 1850.10    99.3 1837.67   149.0 1811.01
   168.9 1797.58   203.6 1775.80   228.5 1762.55   248.4 1749.75   253.3 1745.97
   268.2 1729.95   273.2 1725.76   317.9 1704.52   342.7 1688.41   362.6 1672.64
   376.7 1664.37   382.5 1662.25   387.4 1662.33   391.7 1663.49   437.1 1695.12
   461.9 1707.29   471.9 1711.15   486.8 1720.08   521.5 1744.58   526.5 1747.09
   536.4 1749.73   581.2 1779.63   606.0 1794.63   680.5 1830.40   715.3 1846.06
#Mann= 3 , 0 , 0
       0     0.1       0   376.7   0.045       0   391.7     0.1       0
Bank Sta=   376.7,   391.7
Exp/Cntr=0.3,0.1

Type RM Length L Ch R = 1 ,638,175.6,173.8,171.8
XS GIS Cut Line= 2
     1861248.934      193950.516     1861206.689      194751.811
#Sta/Elev= 30
       0 1853.67   124.6 1800.89   154.5 1783.98   169.4 1777.64   184.4 1768.20
   199.4 1761.93   219.3 1750.39   254.2 1734.45   294.0 1713.48   324.0 1694.08
   348.9 1682.66   368.8 1668.79   378.8 1658.96   385.3 1655.46   388.7 1655.04
   400.3 1657.14   413.7 1663.72   433.6 1679.16   463.5 1686.28   493.4 1698.27
   498.4 1701.53   528.3 1727.28   553.2 1738.77   568.2 1742.17   598.1 1759.20
   667.8 1792.70   717.7 1812.22   747.6 1822.15   777.5 1829.10   802.4 1833.03
#Mann= 3 , 0 , 0
       0     0.1       0   385.3   0.045       0   400.3     0.1       0
Bank Sta=   385.3,   400.3
Exp/Cntr=0.3,0.1

Type RM Length L Ch R = 1 ,464.2,203.4,206.5,209.7
XS GIS Cut Line= 3
     1861046.060      193895.669     1861055.341      194350.658
     1861072.523      194805.318
#Sta/Elev= 30
       0 1862.97   103.9 1848.67   123.7 1843.50   138.5 1835.10   173.1 1812.33
   188.0 1799.57   227.5 1769.75   237.4 1765.15   267.1 1747.50   331.4 1707.58
   380.9 1682.59   405.6 1671.51   420.5 1666.23   445.2 1644.22   456.9 1637.03
   465.1 1634.82   471.9 1637.31   505.1 1662.82   520.1 1672.16   535.1 1675.57
   560.1 1686.68   570.1 1688.51   600.1 1698.50   630.1 1706.15   640.1 1711.34
   670.1 1731.18   675.1 1733.12   710.1 1736.41   875.1 1811.29   910.1 1829.45
#Mann= 3 , 0 , 0
       0     0.1       0   456.9   0.045       0   471.9     0.1       0
Bank Sta=   456.9,   471.9
Exp/Cntr=0.3,0.1

Type RM Length L Ch R = 1 ,257.7,89.8,92.7,95.2
XS GIS Cut Line= 2
     1860893.442      193956.724     1860805.856      194771.494
#Sta/Elev= 30
       0 1753.42    40.0 1743.98    80.0 1740.98    94.9 1741.47   114.9 1746.39
   139.9 1738.50   164.9 1720.41   199.9 1707.19   214.9 1697.44   234.8 1690.26
   269.8 1672.39   284.8 1667.96   319.8 1649.14   329.8 1642.08   349.8 1619.82
   370.2 1611.51   384.8 1608.96   385.2 1609.06   399.7 1614.00   434.7 1635.63
   464.7 1649.02   479.7 1653.78   509.7 1669.86   549.6 1712.89   569.6 1729.87
   594.6 1740.44   609.6 1752.99   649.6 1779.91   749.5 1836.89   819.5 1881.90
#Mann= 3 , 0 , 0
       0     0.1       0   370.2   0.045       0   385.2     0.1       0
Bank Sta=   370.2,   385.2
Exp/Cntr=0.3,0.1

Type RM Length L Ch R = 1 ,165.1,131.1,130.1,129.5
XS GIS Cut Line= 4
     1860787.531      194122.541     1860786.114      194223.130
     1860737.945      194431.393     1860701.109      194599.986
#Sta/Elev= 30
       0 1652.95     9.6 1651.06    24.0 1650.23    33.5 1648.25    47.9 1643.47
    62.3 1641.80    81.4 1638.28    86.2 1637.72   100.6 1637.82   120.5 1634.75
   135.4 1630.98   160.2 1619.76   175.2 1612.21   195.1 1606.27   200.0 1605.58
   210.1 1606.89   229.8 1610.01   264.6 1626.63   284.5 1633.54   299.4 1637.22
   304.4 1639.52   314.4 1645.47   339.0 1658.20   363.7 1671.93   383.4 1684.89
   432.7 1714.30   452.4 1727.35   457.4 1729.82   472.1 1734.71   486.9 1742.74
#Mann= 3 , 0 , 0
       0     0.1       0   195.1   0.045       0   210.1     0.1       0
Bank Sta=   195.1,   210.1
Exp/Cntr=0.3,0.1

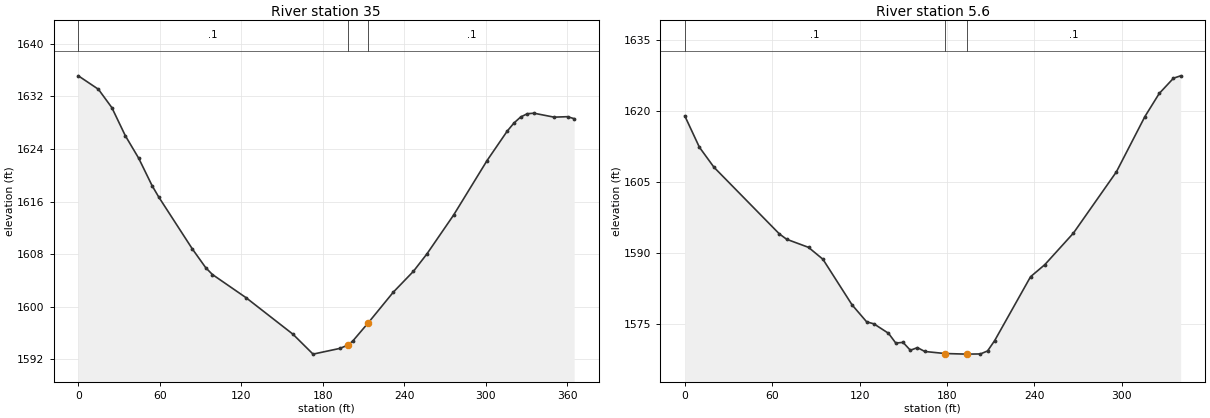
Type RM Length L Ch R = 1 ,35,20.7,29.4,35.2
XS GIS Cut Line= 3
     1860730.861      194114.040     1860643.022      194262.799
     1860604.770      194451.227
#Sta/Elev= 30
       0 1635.14    14.8 1633.09    24.7 1630.29    34.6 1626.02    44.4 1622.61
    54.3 1618.42    59.2 1616.69    83.9 1608.80    93.8 1605.93    98.7 1604.90
   123.4 1601.38   158.0 1595.81   172.8 1592.78   192.5 1593.65   198.6 1594.17
   202.3 1594.84   213.6 1597.59   231.9 1602.22   246.7 1605.39   256.6 1608.03
   276.3 1613.96   300.9 1622.25   315.7 1626.72   320.7 1627.96   325.6 1628.87
   330.5 1629.37   335.4 1629.45   350.2 1628.85   360.1 1628.92   365.0 1628.62
#Mann= 3 , 0 , 0
       0     0.1       0   198.6   0.045       0   213.6     0.1       0
Bank Sta=   198.6,   213.6
Exp/Cntr=0.3,0.1

Type RM Length L Ch R = 1 ,5.6,14.3,5.6,0
XS GIS Cut Line= 4
     1860702.465      194129.778     1860619.135      194271.885
     1860598.302      194303.877     1860579.702      194440.032
#Sta/Elev= 30
       0 1618.93    10.0 1612.33    20.0 1608.10    64.9 1594.02    69.9 1592.89
    84.9 1591.18    94.8 1588.67   114.8 1579.04   124.8 1575.46   129.8 1575.03
   139.8 1573.04   144.8 1570.98   149.8 1571.12   154.8 1569.46   159.7 1570.01
   164.7 1569.20   178.5 1568.77   193.4 1568.64   193.5 1568.64   202.9 1568.68
   207.8 1569.31   212.7 1571.51   237.3 1584.98   247.1 1587.53   266.7 1594.18
   296.2 1607.11   315.8 1618.80   325.6 1623.66   335.4 1626.89   340.3 1627.39
#Mann= 3 , 0 , 0
       0     0.1       0   178.5   0.045       0   193.5     0.1       0
Bank Sta=   178.5,   193.5
Exp/Cntr=0.3,0.1